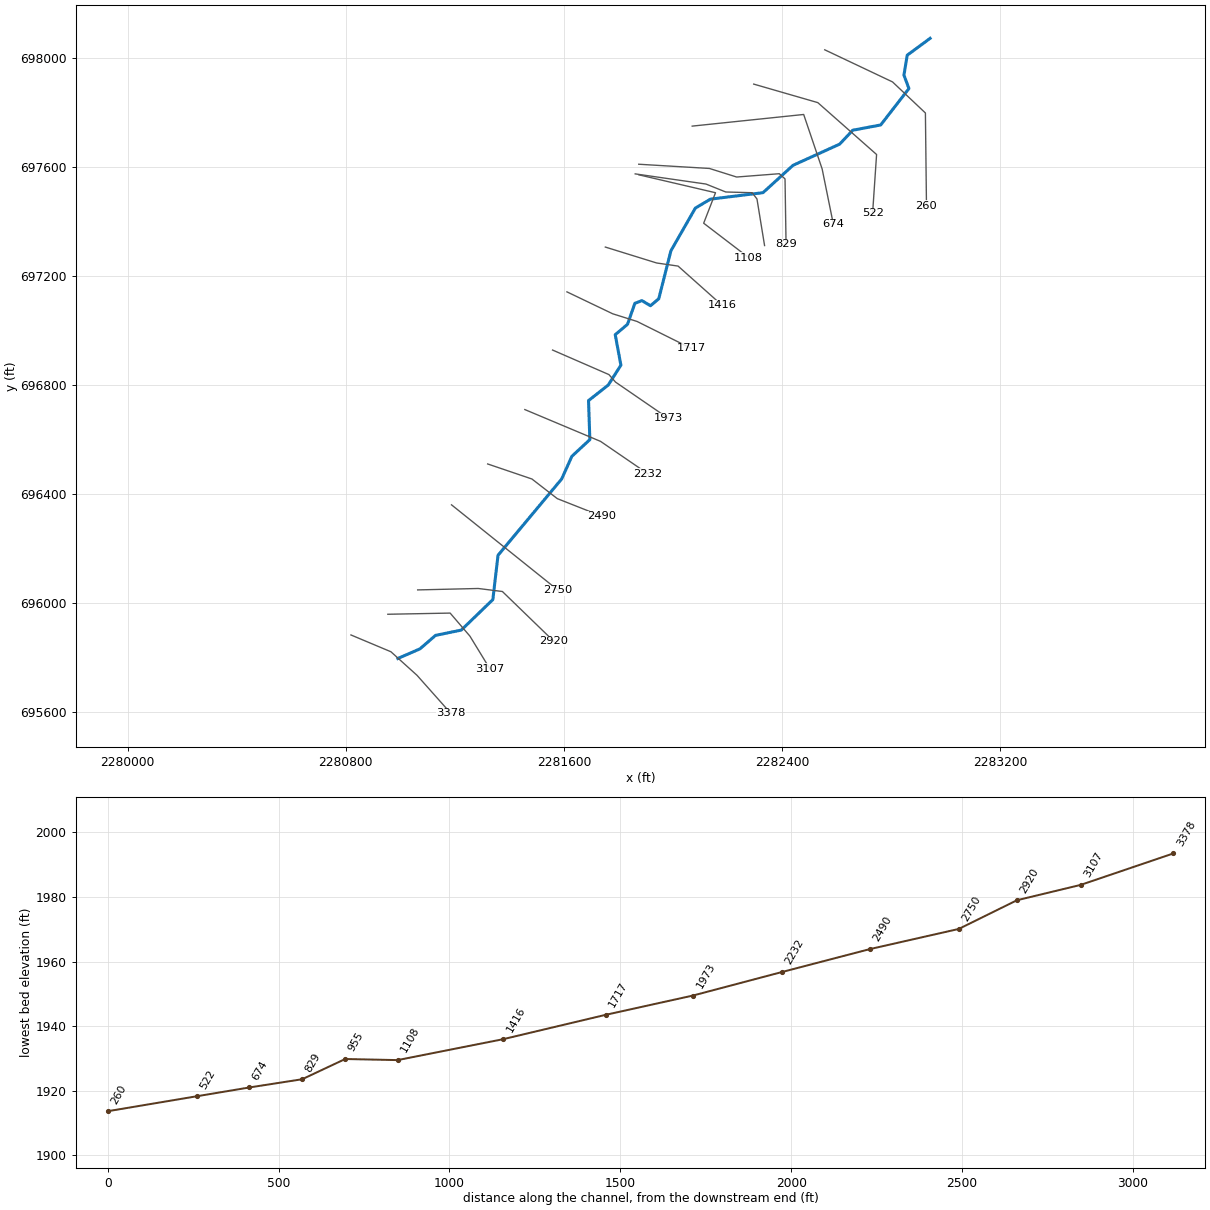
--- MTHIASRN.prj (project) ---

Proj Title=MTHIASRN
Current Plan=p01
Default Exp/Contr=0,0
English Units
Geom File=g01
Flow File=f01
Plan File=p01
BEGIN DESCRIPTION:
----------MODEL BY WOOD PLC 2022----------
AFH study
Randolph County, WV
HEC-RAS Version: RAS 6.2
Vertical Datum: NAVD88
Projection: NAD 1983 StatePlane West Virginia S FIPS 4702 (US Feet)
Terrain: 1-meter LIDAR (FEMA Region III 3DEP collected 2016-2018)
Land Use: 2019 NLCD
Hydrologic Method:
WV SIR2010-5033 regression equations
Additional Model Notes:
None
END DESCRIPTION:
DSS Export Rating Curves= 0
DSS Export Rating Curve Sorted= 0
DSS Export Volume Flow Curves= 0
DXF OffsetX= 0
DXF OffsetY= 0
DXF ScaleX= 0
DXF ScaleY= 0

--- MTHIASRN.p01 (plan) ---

Plan Title=Floodplain
Program Version=6.20
Short Identifier=Floodplain
Geom File=g01
Flow File=f01
Subcritical Flow
K Sum by GR= 0
Std Step Tol= 0.01
Critical Tol= 0.01
Num of Std Step Trials= 20
Max Error Tol= 0.3
Flow Tol Ratio= 0.001
Split Flow NTrial= 30
Split Flow Tol= 0.02
Split Flow Ratio= 0.02
Log Output Level= 0
Friction Slope Method= 1
Unsteady Friction Slope Method= 2
Unsteady Bridges Friction Slope Method= 1
Parabolic Critical Depth
Global Vel Dist= 0 , 0 , 0
Global Log Level= 0
CheckData=True
Encroach Param=-1 ,0,0, 0
Mapping Interval=1HOUR
Computation Time Step Use Courant=        0
Computation Time Step Use Time Series=    0
Computation Time Step Count To Double=0
Computation Time Step Max Doubling=0
Computation Time Step Max Halving=0
Computation Time Step Residence Courant=0
Run HTab= 0
Run UNet= 0
Run Sediment= 0
Run PostProcess= 0
Run WQNet= 0
Run RASMapper=-1
UNET Theta= 0
UNET Theta Warmup= 0
UNET ZTol= 0
UNET ZSATol= 0
UNET MxIter= 0
UNET Max Iter WO Improvement= 0
UNET MaxInSteps= 0
UNET DtIC= 0
UNET DtMin= 0
UNET MaxCRTS= 0
UNET WFStab= 0
UNET SFStab= 0
UNET WFX= 1
UNET SFX= 1
UNET Gravity=32.174
UNET 1D Methodology=Finite Difference
UNET DSS MLevel= 1
UNET Pardiso=0
UNET DZMax Abort= 0
UNET Use Existing IB Tables= 0
UNET Froude Reduction=False
UNET Froude Limit= 0
UNET Froude Power= 0
UNET D1 Cores= 0
UNET WindReference=Eulerian
UNET WindDragFormulation=Hsu (1988)
UNET D2 Coriolis=0
UNET D2 Cores= 0
UNET D2 Theta= 1
UNET D2 Theta Warmup= 1
UNET D2 Z Tol= 0.01
UNET D2 Volume Tol= 0.01
UNET D2 Max Iterations= 20
UNET D2 Equation= 0
UNET D2 RampUpFraction=0.1
UNET D2 TimeSlices= 1
UNET D2 Turbulence Formulation=Non-Conservative (original)
UNET D2 Eddy Viscosity=0.3
UNET D2 Transverse Eddy Viscosity=0.1
UNET D2 Smagorinsky Mixing=0
UNET D2 BCVolumeCheck=0
UNET D2 Cores=0
UNET D2 SolverType=PARDISO (Direct)
UNET D2 Minimum Iterations= 2147483647
UNET D2 Maximum Iterations= 2147483647
UNET D2 Restart Number= 10
UNET D2 Relaxation Coeff=1.3
UNET D2 SOR Precondition Iterations= 10
UNET D2 ILUT Maximum Fill= 8
UNET D2 ILUT Tolerance=1E-08
UNET D1D2 MaxIter= 0
UNET D1D2 ZTol=0.01
UNET D1D2 QTol=0.1
UNET D1D2 MinQTol=1
Write IC File= 0
Write IC File at Fixed DateTime=0
Write IC File at Sim End=0
Echo Input=False
Echo Parameters=False
Echo Output=False
Write Detailed= 0
HDF Write Warmup=0
HDF Write Time Slices=0
HDF Flush=0
HDF Compression= 1
HDF Chunk Size= 1
HDF Spatial Parts= 1
HDF Use Max Rows=0
HDF Fixed Rows= 1
Calibration Method= 0
Calibration Iterations= 20
Calibration Max Change=0.05
Calibration Tolerance=0.2
Calibration Maximum=1.5
Calibration Minimum=0.5
Calibration Optimization Method= 1
WQ AD Non Conservative
WQ ULTIMATE=-1
WQ Max Comp Step=1HOUR
WQ Output Interval=15MIN
WQ Output Selected Increments= 0
WQ Output face flow=0
WQ Output face velocity=0
WQ Output face area=0
WQ Output face dispersion=0
WQ Output cell volume=0
WQ Output cell surface area=0
WQ Output cell continuity=0
WQ Output cumulative cell continuity=0
WQ Output face conc=0
WQ Output face dconc_dx=0
WQ Output face courant=0
WQ Output face peclet=0
WQ Output face adv mass=0
WQ Output face disp mass=0
WQ Output cell mass=0
WQ Output cell source sink temp=0
WQ Output nsm pathways=0
WQ Output nsm derived pathways=0
WQ Create Restart=0
WQ Fixed Restart=0
WQ System Summary=0
WQ Write To DSS=0
Sorting and Armoring Iterations= 10
XS Update Threshold= 0.02
Bed Roughness Predictor= 0
Hydraulics Update Threshold= 0.02
Energy Slope Method= 1
Volume Change Method= 1
Sediment Retention Method= 0
Sediment TS Multiplier= 1
Warm Up Method= 0
XS Weighting Method= 0
Number of US Weighted Cross Sections= 1
Number of DS Weighted Cross Sections= 1
Upstream XS Weight=0
Main XS Weight=1
Downstream XS Weight=0
Number of DS XS's Weighted with US Boundary= 1
Upstream Boundary Weight= 1
Weight of XSs Associated with US Boundary= 0
Number of US XS's Weighted with DS Boundary= 1
Downstream Boundary Weight= 0.5
Weight of XSs Associated with DS Boundary= 0.5
Percentile Method= 0
Sediment Output Level= 3
Mass or Volume Output= 0
Output Increment Type= 1
Profile and TS Output Increment= 1
Transport Output Increment 1
XS Output Flag= 0
XS Output Increment= 10
Read HDF5 Sediment Hotstart= 0
Sediment Hotstart Type= 0
Write Gradation File= 0
Read Gradation Hotstart= 0
Write HDF5 File= 1
Write Binary Output= 1
Write DSS Sediment File= 0
DSS Sediment Output Type= 1
SV Curve= 0
Specific Gage Flag= 0
Subcell Erosion Methods= 0
Subcell Deposition Methods= 0
Advection Scheme= 1
Matrix Solver= 0
Implicit Weighting Factor= 1
Maximum Outer Loop Convergence Iterations= 5
Convergence Maximum Absolute= 0.001
Convergence RMSE= 0.0001
Grain Fractions Max Abs Error= 0.001
Max Subgrid Regions= 1
Max Subgrid Length Scale= 3.402823E+38
Initial Layer Thickness= 3.402823E+38
Min Layer Thickness= 3.402823E+38
Max Layer Thickness= 3.402823E+38
Number of Layers= 5

--- MTHIASRN.f01 (steady flow) ---

Flow Title=Flow
Program Version=6.20
Number of Profiles= 1
Profile Names=P100yr
River Rch & RM=MTHIASRN,Main,3378
     340
Boundary for River Rch & Prof#=MTHIASRN,Main            , 1
Up Type= 0
Dn Type= 3
Dn Slope=0.01771
DSS Import GetInterval= 0
DSS Import GetPeak= 0
DSS Import FillOption= 0

--- MTHIASRN.g01 (geometry) ---

Geom Title=Geometry
Program Version=6.20

River Reach=MTHIASRN        ,Main
Reach XY= 30
     2280990.916      695796.157     2281072.166      695831.574
     2281129.111       695880.88     2281223.555      695900.324
     2281339.263      696012.071     2281358.277       696174.63
     2281591.637      696454.522     2281629.171      696537.698
     2281695.083      696598.935     2281690.222      696741.991
     2281762.444      696798.935     2281808.972      696871.903
     2281788.139      696983.657     2281833.277      697021.852
     2281860.122      697098.693     2281886.055      697108.657
     2281917.569      697089.907     2281947.861      697115.602
     2281992.305      697291.296     2282082.018      697448.001
     2282137.444       697480.88     2282330.045      697504.596
     2282440.459      697605.055     2282611.232      697682.642
     2282659.337      697733.613     2282761.728      697752.894
     2282865.344      697886.508     2282847.049      697935.661
     2282859.025      698008.763     2282943.092      698070.657

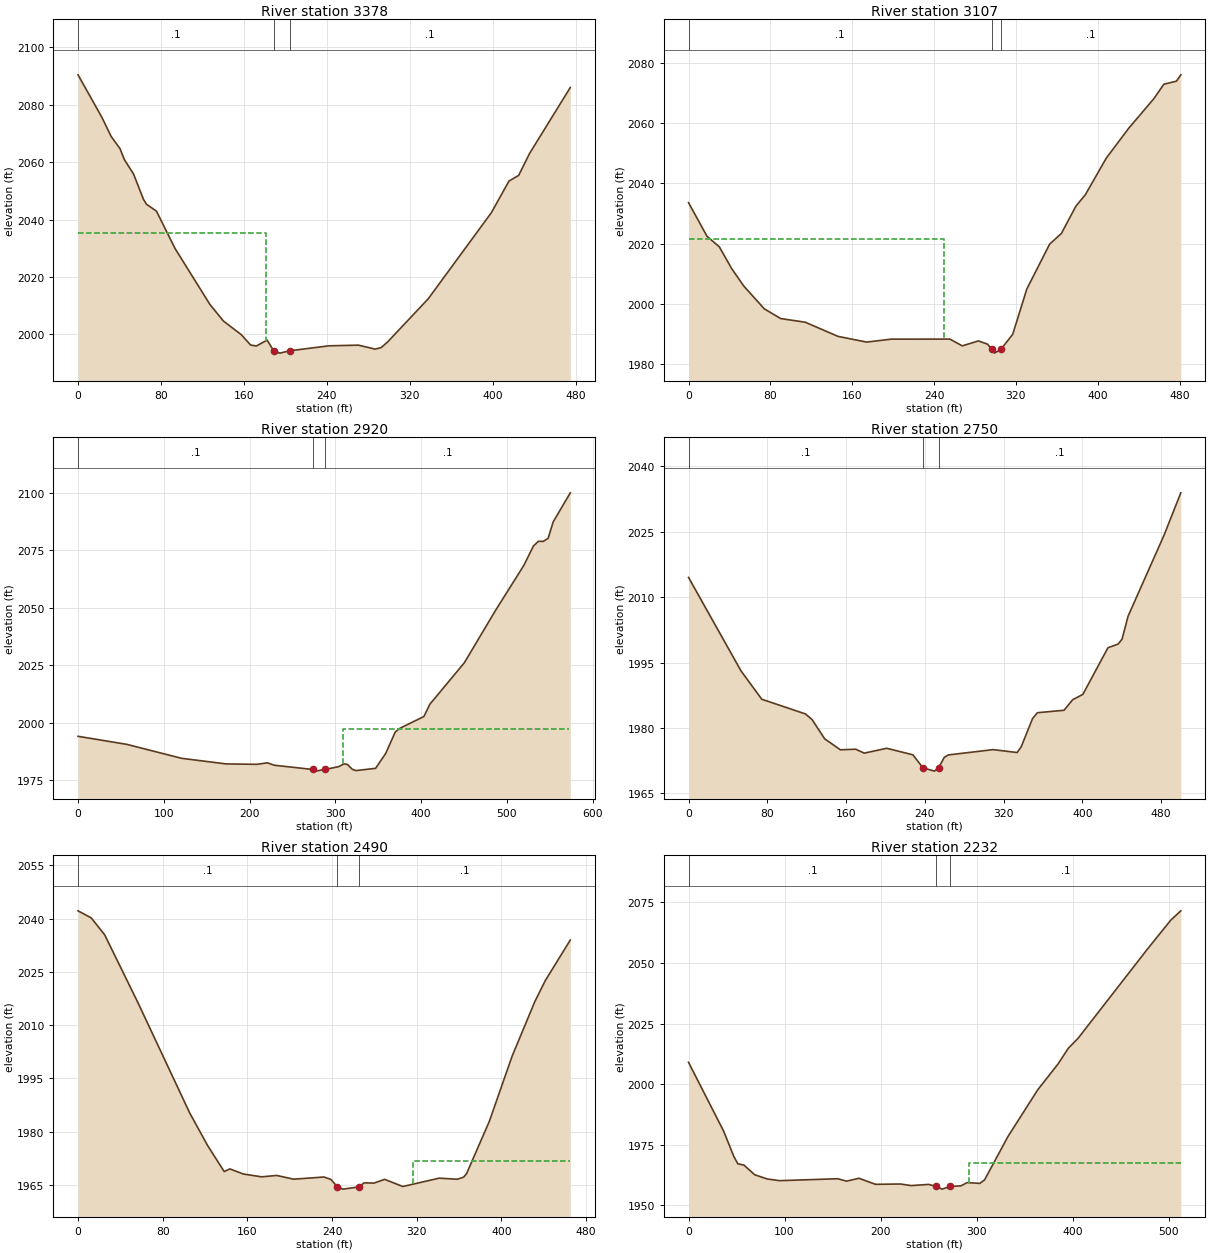
Type RM Length L Ch R = 1 ,3378    ,271.5,271.4,268.1
XS GIS Cut Line= 4
2280818.88126651695882.4583320622280965.45959886695820.860355587
2281061.27556051695734.3581933212281185.27161204695594.854554888
#Sta/Elev= 30
       0 2090.46    23.1 2075.59    31.8 2069.08    40.5 2064.73    44.8 2060.85
    53.5 2055.92    63.1 2047.08    66.1 2045.33    75.6 2042.98    93.6 2029.92
   127.2 2010.44   140.2 2004.67   157.6 1999.86   166.4  1996.3     172 1995.97
   182.4 1998.02  188.651994.296   194.7 1993.48  203.981994.297   242.1 1996.03
   270.4 1996.26   286.6 1994.87   292.4 1995.44   298.5 1997.36   337.8 2012.45
   398.6 2042.43   415.6 2053.45   424.9 2055.41   435.5  2063.1   474.7 2086.04
#Mann= 3 ,-1,0
       0      .1       0  188.65    .045       0  203.98      .1       0
#XS Ineff= 2 , 0
          181.59 2035.38
Permanent Ineff=
       F       F
Bank Sta=188.65,203.98
XS Rating Curve= 0 ,0
Exp/Cntr(USF)=0,0
Exp/Cntr=0.3,0.1

Type RM Length L Ch R = 1 ,3107    ,179.9,186.4,189.8
XS GIS Cut Line= 4
2280954.10564944  695958.38925072281182.66582188695962.673894824
 2281255.1914702695878.1415075512281328.82392721695757.599313842
#Sta/Elev= 30
       0 2033.59    18.1 2022.42    30.1 2018.95    42.1 2011.77    54.1 2005.92
    74.1  1998.4    90.1 1995.18   114.1 1993.97   146.1 1989.28   174.1 1987.39
   198.1 1988.36   255.5 1988.38   267.6 1986.13   283.3 1987.78   292.3  1986.7
   296.41985.024   299.1 1983.73  305.47 1985.03   316.9 1989.97   330.7 2004.99
     353 2019.85   364.5 2023.39   378.6 2032.39     388 2036.27   408.3 2048.31
   430.2  2058.2   454.9 2068.05   464.6 2072.82     477 2073.85   481.2 2075.94
#Mann= 3 ,0,0
       0      .1       0   296.4    .045       0  305.47      .1       0
#XS Ineff= 2 , 0
          250.18 2021.42
Permanent Ineff=
       F       F
Bank Sta=296.4,305.47
XS Rating Curve= 0 ,0
Exp/Cntr(USF)=0,0
Exp/Cntr=0.3,0.1

Type RM Length L Ch R = 1 ,2920    ,176.2,170.4,167.9
XS GIS Cut Line= 4
2281063.55467343696047.6717090092281285.68208502696052.895732311
2281374.29245497696041.8443211612281562.79956388 695859.29276095
#Sta/Elev= 30
       0 1994.11    56.8 1990.62   120.7 1984.55   172.7 1982.11   208.7 1981.94
   220.7 1982.59   228.7 1981.55   273.7  1979.7   277.1 1978.98  287.66 1979.69
   303.7  1980.9   310.2 1982.16   314.1 1981.87   319.7 1979.79   323.9 1979.21
   346.9  1980.2   358.7 1986.67   369.9 1996.03   375.4 1997.63   403.2  2002.7
   410.2 2008.05   450.4 2026.09   486.7 2048.79   519.8 2068.41   530.9 2076.79
   536.7 2078.84   542.4 2078.81   548.1 2080.15   553.9 2087.23   573.9 2099.91
#Mann= 3 ,0,0
       0      .1       0   273.7    .045       0  287.66      .1       0
#XS Ineff= 1 ,-1
  309.07   572.41997.121
Permanent Ineff=
       F
Bank Sta=273.7,287.66
XS Rating Curve= 0 ,0
Exp/Cntr(USF)=0,0
Exp/Cntr=0.3,0.1

Type RM Length L Ch R = 1 ,2750    ,259.9,260.1,260.4
XS GIS Cut Line= 2
2281187.74510236696359.6916036552281577.88579692696046.977295629
#Sta/Elev= 30
       0 2014.53    53.3 1993.09    74.4 1986.58   118.8 1983.21   125.5 1981.91
   138.3  1977.5   154.3 1974.98   169.7 1975.12   178.5 1974.22   201.3 1975.33
   227.9 1973.83  238.051970.858   249.7 1970.09  253.921970.859   259.8 1973.24
   263.9 1973.81   309.4 1975.02   333.8 1974.36   337.9 1975.69   349.4 1982.14
   354.3 1983.49   381.4 1984.05   390.2 1986.48   400.5 1987.69     426  1998.4
   436.3 1999.23   440.3 2000.36   446.5 2005.66     483 2024.23     500 2033.94
#Mann= 3 ,-1,0
       0      .1       0  238.05    .045       0  253.92      .1       0
Bank Sta=238.05,253.92
XS Rating Curve= 0 ,0
Exp/Cntr(USF)=0,0
Exp/Cntr=0.3,0.1

Type RM Length L Ch R = 1 ,2490    ,255.9,257.7,259.8
XS GIS Cut Line= 4
2281320.30161538696509.6319909122281482.68905364696454.441553206
2281575.62884154696382.4421114122281739.34717971696317.704276368
#Sta/Elev= 30
       0 2042.17    12.5 2040.18    25.2 2035.41      57 2016.08   105.5  1985.3
   122.4 1976.14   138.1  1968.8   143.5 1969.54   156.2  1968.1   173.4 1967.31
   187.7  1967.7   203.7 1966.65   232.4 1967.26   238.9 1966.59   245.11964.465
   250.4 1963.85  265.24 1964.47   270.4 1965.63   279.6 1965.54   289.7  1966.6
   306.9 1964.59   341.3 1966.94   358.5 1966.63   364.4 1967.24   367.1 1968.21
   388.6 1982.92   410.1 2001.24   431.6 2016.63   441.5 2022.54   465.1 2033.95
#Mann= 3 ,0,0
       0      .1       0   245.1    .045       0  265.24      .1       0
#XS Ineff= 2 , 0
                          316.02         1971.88
Permanent Ineff=
       F       F
Bank Sta=245.1,265.24
XS Rating Curve= 0 ,0
Exp/Cntr(USF)=0,0
Exp/Cntr=0.3,0.1

Type RM Length L Ch R = 1 ,2232    ,262.4,259.2,255.4
XS GIS Cut Line= 3
2281456.64114034696709.0971696672281734.36880897696592.428338465
2281908.76224463696472.985983335
#Sta/Elev= 30
       0 2009.05    36.7 1980.55    47.2 1970.17    51.4 1967.16    57.6 1966.69
    68.9 1962.67    81.9 1960.93    94.9 1960.23   155.4 1961.03   164.6 1960.03
   177.4 1961.22   194.7 1958.72   220.8 1958.85   231.8  1958.2   250.1 1958.69
  257.961957.845   264.1 1956.74  272.261957.844   283.6 1958.09   290.2 1959.44
   303.4 1959.11   308.3 1960.59   332.5 1978.36   363.6  1997.7   384.9 2008.44
   395.5 2014.87   405.6 2018.95   477.5 2055.58   502.2 2067.72   512.6 2071.55
#Mann= 3 ,-1,0
       0      .1       0  257.96    .045       0  272.26      .1       0
#XS Ineff= 2 , 0
                          292.49         1967.56
Permanent Ineff=
       F       F
Bank Sta=257.96,272.26
XS Rating Curve= 0 ,0
Exp/Cntr(USF)=0,0
Exp/Cntr=0.3,0.1

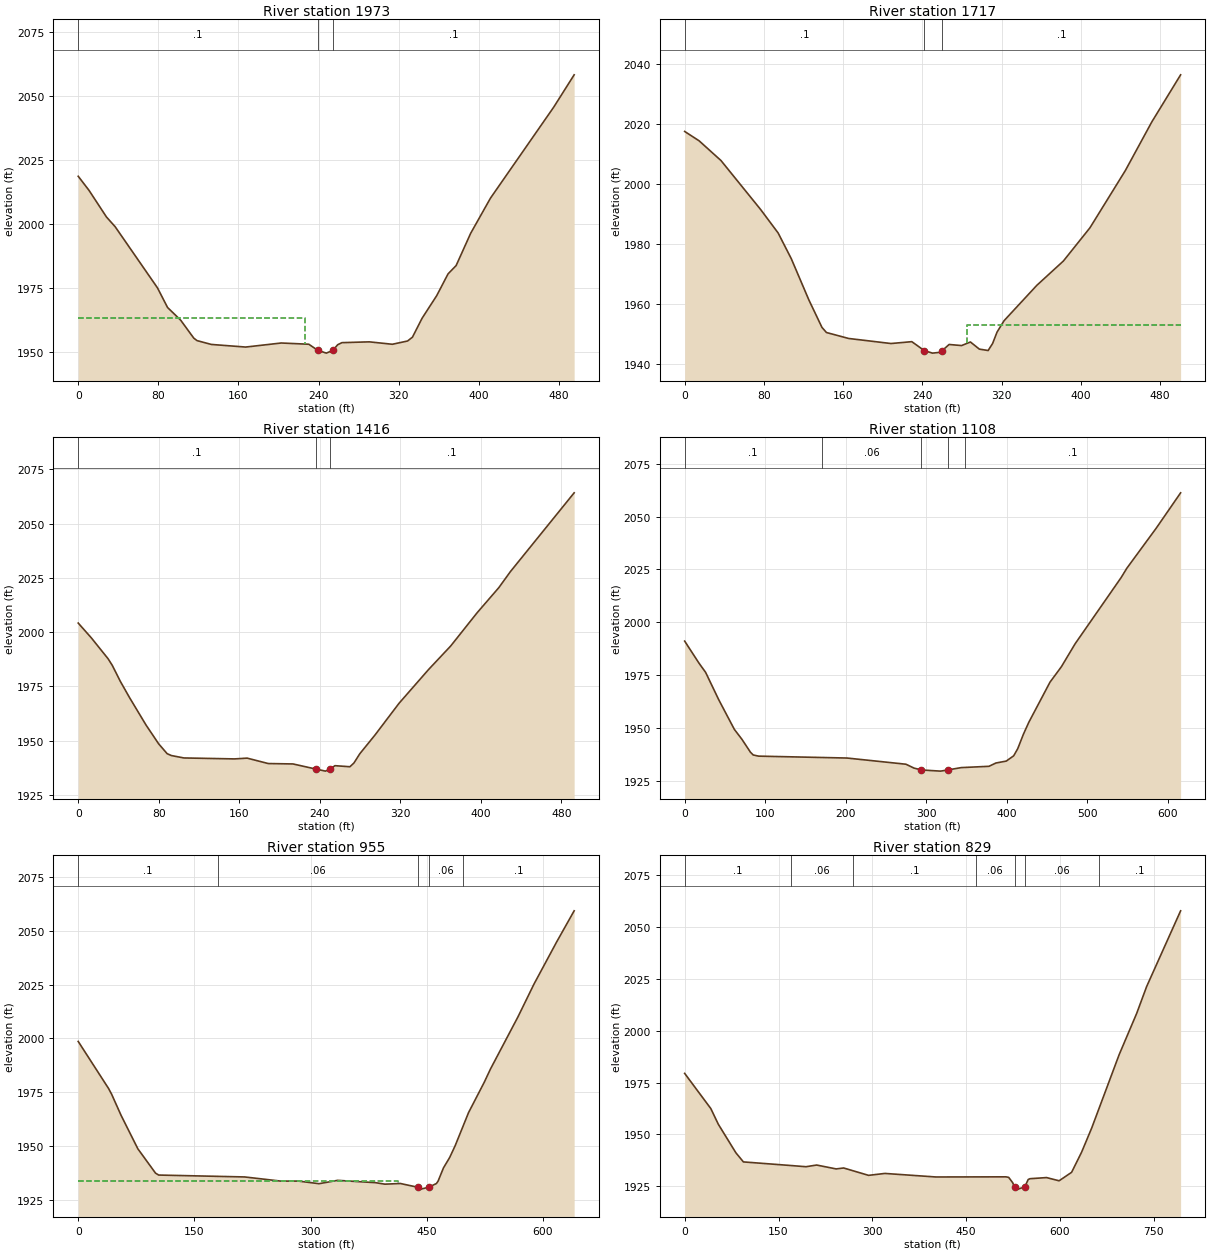
Type RM Length L Ch R = 1 ,1973    ,250.2,256.1,258
XS GIS Cut Line= 4
2281558.35483355696927.408132982 2281765.0049763696837.428375502
2281789.34258029696809.7721148412281981.31133421696677.876192753
#Sta/Elev= 30
       0 2018.52    10.7 2013.07    28.2 2002.63    36.9 1998.82    79.1 1974.98
    89.2  1967.3   102.3 1962.35   115.4 1955.33   118.6 1954.38   132.9 1952.88
   167.2 1951.86   202.7 1953.44   230.2 1952.96   239.1  1950.6   247.7 1949.49
  254.31 1950.59     259 1952.76   263.3 1953.58   290.6 1953.89   313.6 1952.95
   328.8 1954.22   333.7 1955.73   343.3 1963.11   357.9 1971.93   369.2 1980.41
   377.3 1983.68   391.8 1996.26   411.6    2010   474.7 2045.49   495.1 2058.11
#Mann= 3 ,0,0
       0      .1       0   239.1    .045       0  254.31      .1       0
#XS Ineff= 2 , 0
          226.23 1963.04
Permanent Ineff=
       F       F
Bank Sta=239.1,254.31
XS Rating Curve= 0 ,0
Exp/Cntr(USF)=0,0
Exp/Cntr=0.3,0.1

Type RM Length L Ch R = 1 ,1717    ,298.8,300.4,298.8
XS GIS Cut Line= 4
2281611.04667166 697140.804130162281778.86030288697060.418221841
2281868.18466316697032.3059866282282066.15445955696933.736746424
#Sta/Elev= 30
       0 2017.36    14.6 2014.24    36.7 2007.66    76.7 1991.36    94.4 1983.53
   107.7 1974.95   125.4 1961.25   138.7 1952.05   143.2 1950.37   165.5 1948.39
   208.4  1946.7   229.4 1947.32     242 1944.35   250.3  1943.5   258.7  1943.8
  260.081944.342   267.1 1946.38   279.7 1946.02   288.6 1947.21   297.6 1944.84
   306.5 1944.37     311 1946.71   315.5 1950.51   322.6 1954.31   355.7  1966.1
   382.5 1974.19   409.3 1985.25     445 2004.29   471.8 2020.54   500.9 2036.23
#Mann= 3 ,-1,0
       0      .1       0     242    .045       0  260.08      .1       0
#XS Ineff= 1 ,-1
  284.98500.8685 1952.85
Permanent Ineff=
       F
Bank Sta=242,260.08
XS Rating Curve= 0 ,0
Exp/Cntr(USF)=0,0
Exp/Cntr=0.3,0.1

Type RM Length L Ch R = 1 ,1416    ,335.4,308.3,287.9
XS GIS Cut Line= 4
2281751.87043176697305.098856531 2281940.0916274697246.735587197
2282018.65624429697235.3557441292282180.03062885697091.577840093
#Sta/Elev= 30
       0 2004.19    12.9 1997.44    29.6 1987.79    33.8 1984.73    41.7 1977.45
    50.6 1970.14    67.3 1957.24    79.9 1948.54    88.3 1944.01    92.5 1943.13
     105 1942.02   155.3 1941.58   167.8 1941.94   188.8 1939.44   213.3 1939.26
  235.77 1936.93   245.6 1935.95  250.26 1936.93     255 1938.46   269.9 1937.97
   273.9 1939.72   279.7 1943.96   294.6 1952.48   318.7 1967.23   348.1 1982.83
   369.9 1993.58   396.3 2008.98   417.8 2020.52   429.2 2027.85   492.6 2064.21
#Mann= 3 ,0,0
       0      .1       0  235.77    .045       0  250.26      .1       0
Bank Sta=235.77,250.26
XS Rating Curve= 0 ,0
Exp/Cntr(USF)=0,0
Exp/Cntr=0.3,0.1

Type RM Length L Ch R = 1 ,1108    ,137.5,153.1,159.5
XS GIS Cut Line= 4
2281874.89513239697570.0708239722282155.96743078697504.402439621
2282112.54192352697392.6075633382282277.22789482697266.702911021
#Sta/Elev= 30
       0 1991.06    17.7 1980.67      26 1976.27    42.4 1963.23    61.7 1949.26
    71.1 1944.56    81.7 1938.44    85.1 1937.15    91.7 1936.59   201.6 1935.69
   274.8 1932.76   284.8 1930.92   294.1 1930.04   317.8 1929.49   326.4 1930.03
   343.5 1931.16   377.9 1931.77   386.5 1933.33   399.4 1934.25   408.6 1936.75
   413.6 1940.11   420.8 1947.08   427.4 1952.63   453.7 1971.63   467.8 1978.91
   484.9 1989.81     542 2021.14   549.1 2025.57   585.5 2044.49   615.9 2061.29
#Mann= 5 ,-1,0
       0      .1       0     170     .06       0   294.1    .045       0
   326.4     .06       0  348.64      .1       0
Bank Sta=294.1,326.4
XS Rating Curve= 0 ,0
Exp/Cntr(USF)=0,0
Exp/Cntr=0.3,0.1

Type RM Length L Ch R = 1 ,955     ,124.5,126.1,127.4
XS GIS Cut Line= 6
2281861.37697721697573.531013799 2282121.1316499 697536.19552815
  2282193.521109697507.1075263222282290.37093327697504.463162519
2282308.02206166697481.4241428892282335.85882308697310.679297934
#Sta/Elev= 30
       0 1998.58    39.2 1976.67    43.2 1973.96    55.4 1964.13      77  1948.6
    99.8 1937.28   103.9 1936.38   214.8  1935.5   261.5 1933.56   284.2 1933.57
   310.9 1932.36   334.9 1933.91   383.9 1932.83   395.9 1932.14   415.9 1932.45
   438.4  1930.7   442.3 1929.83   452.4  1930.7   462.4 1932.44   464.6 1933.59
   471.5 1939.71   479.6 1944.61   486.7 1950.13   503.9 1965.46   524.2 1979.61
   532.3 1985.83   567.6 2009.97   588.3 2025.24   617.4 2044.76   640.2 2059.38
#Mann= 5 ,-1,0
       0      .1       0     180     .06       0   438.4    .045       0
   452.4     .06       0  497.18      .1       0
#XS Ineff= 2 , 0
          412.24 1933.72
Permanent Ineff=
       F       F
Bank Sta=438.4,452.4
XS Rating Curve= 0 ,0
Exp/Cntr(USF)=0,0
Exp/Cntr=0.3,0.1

Type RM Length L Ch R = 1 ,829     ,160.1,155,152.2
XS GIS Cut Line= 6
2281874.43137784697608.9071567062282133.62626887697593.403155989
2282233.45100242697562.0013358332282389.88011541697574.148600667
2282410.92086813697555.0929353982282414.69720505697314.866013665
#Sta/Elev= 30
       0 1979.39    41.8 1962.42    53.8 1954.85    81.9 1941.08    93.9 1936.69
     170 1934.94   193.9 1934.37     211 1935.18   242.2 1933.31   254.2 1933.76
     294  1930.2   320.1 1931.13   401.6 1929.42   513.6 1929.49     518 1929.24
   524.3 1926.71  527.61 1924.56   532.8 1923.56   543.8 1924.62   549.2 1928.19
   552.1 1928.59   578.6 1929.13   598.6 1927.58   618.6 1931.67   634.6 1941.39
   650.9 1953.15   694.6 1988.41   722.6 2008.29   738.6  2021.3   792.9 2057.82
#Mann= 7 ,-1,0
       0      .1       0     170     .06       0  269.66      .1       0
  465.39     .06       0  527.61    .045       0   543.8     .06       0
  662.67      .1       0
Bank Sta=527.61,543.8
XS Rating Curve= 0 ,0
Exp/Cntr(USF)=0,0
Exp/Cntr=0.3,0.1

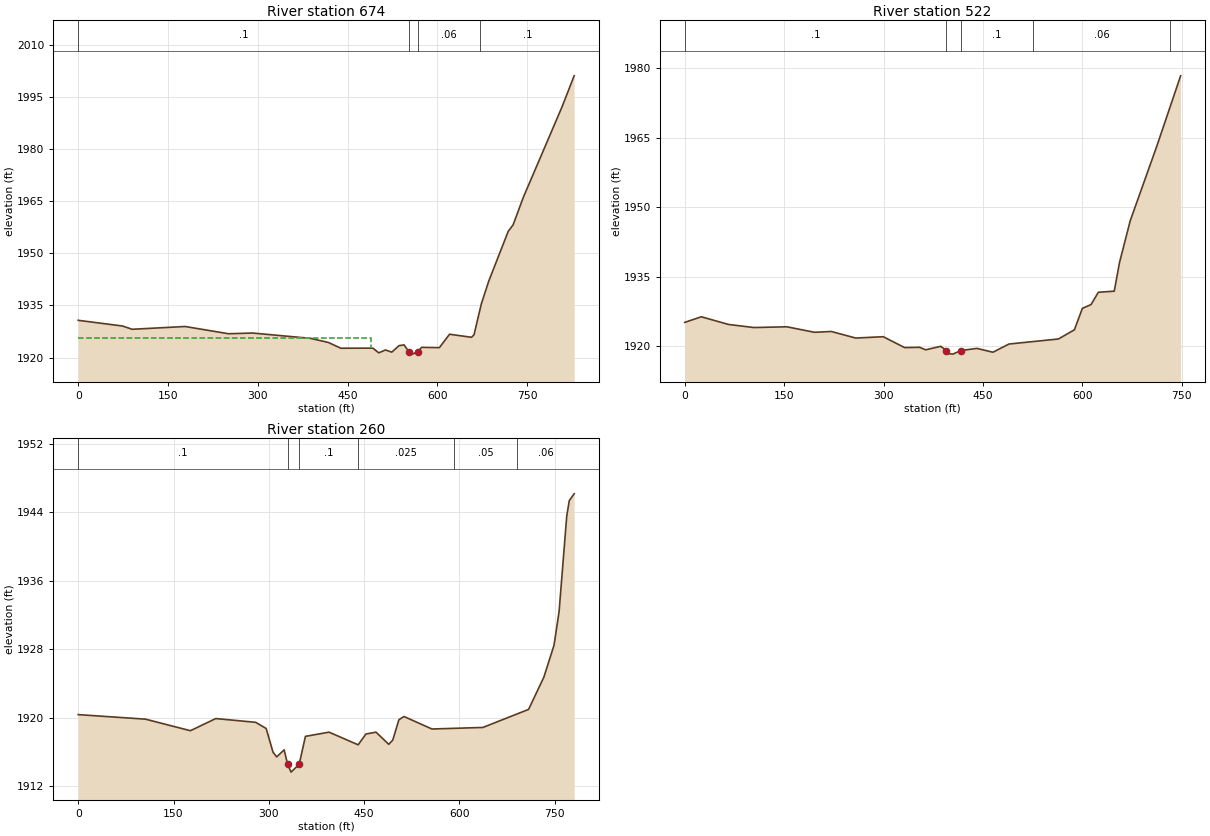
Type RM Length L Ch R = 1 ,674     ,146.5,152.4,156.3
XS GIS Cut Line= 4
2282070.45755835697748.7235815772282479.32861336697791.407865521
2282547.06219482 697591.565811142282588.10384044697389.173955199
#Sta/Elev= 30
       0 1930.73    74.1 1929.09    90.2 1928.15   178.7 1928.95   251.1 1926.87
   291.3 1927.07   387.8 1925.55   417.7 1924.38   438.8 1922.71   492.4 1922.73
   502.1 1921.38   513.4 1922.21   523.9 1921.58   535.9 1923.44   544.4 1923.67
   552.3 1921.75   558.6 1921.01   567.11921.753   573.9 1922.96   603.5 1922.88
   620.4 1926.73   657.2 1925.85   661.3 1926.57   673.5 1935.44   685.8 1941.94
   718.4 1956.28   726.6 1958.16   743.8 1966.13   808.2 1992.01   828.6    2001
#Mann= 4 ,-1,0
       0      .1       0   552.3    .045       0   567.1     .06       0
   672.1      .1       0
#XS Ineff= 2 , 0
           489.6 1925.52
Permanent Ineff=
       F       F
Bank Sta=552.3,567.1
XS Rating Curve= 0 ,0
Exp/Cntr(USF)=0,0
Exp/Cntr=0.3,0.1

Type RM Length L Ch R = 1 ,522     ,262,261.6,260.1
XS GIS Cut Line= 4
2282296.04747175697902.8086727412282531.10151449697834.892314435
2282746.70017552697644.6060999682282732.10079964697429.350115661
#Sta/Elev= 30
       0 1925.16    25.1 1926.37      66 1924.72   104.2 1924.05   154.2 1924.21
   195.8 1923.02   221.1  1923.2     258 1921.78   299.5 1922.07   331.7 1919.72
   354.3 1919.78   363.5 1919.24   386.3    1920  394.681919.083   398.4 1918.42
   404.4 1918.31   416.5 1919.08   440.7 1919.55   464.9 1918.72   489.1 1920.49
   563.7 1921.58   587.8 1923.56   599.8 1928.18   612.9 1929.01   623.9 1931.66
   647.9  1931.9   655.9 1938.12     672  1947.1   712.1  1963.2     748 1978.38
#Mann= 5 ,-1,0
       0      .1       0  394.68    .045       0   416.5      .1       0
  524.67     .06       0  732.23      .1       0
Bank Sta=394.68,416.5
XS Rating Curve= 0 ,0
Exp/Cntr(USF)=0,0
Exp/Cntr=0.3,0.1

Type RM Length L Ch R = 1 ,260     ,,,
XS GIS Cut Line= 4
2282556.53957622698028.6243274072282805.18463139697910.818053281
2282925.77634031697796.854518998 2282929.6976553697457.485474207
#Sta/Elev= 30
       0 1920.38   105.8 1919.85   176.6  1918.5   216.5 1919.92   279.3 1919.48
   295.8 1918.76   306.6 1915.99   312.3 1915.44   324.1 1916.26  329.561914.582
     335 1913.66  347.75 1914.58   357.6 1917.84   394.8 1918.33   440.6 1916.85
   452.7 1918.11   468.7 1918.33   488.7 1916.91     495  1917.4   504.7 1919.78
   512.7 1920.16   556.7  1918.7   636.9 1918.88   708.8 1920.99   732.8 1924.75
   748.8 1928.48   756.8 1932.42   768.8 1943.55   772.8 1945.38   780.5 1946.18
#Mann= 6 ,-1,0
       0      .1       0  329.56    .045       0  347.75      .1       0
  441.06    .025       0  591.06     .05       0  691.06     .06       0
Bank Sta=329.56,347.75
XS Rating Curve= 0 ,0
Exp/Cntr(USF)=0,0
Exp/Cntr=0.3,0.1
LCMann Table=0

Chan Stop Cuts=-1
Use User Specified Reach Order=0
Composite Channel Slope=5